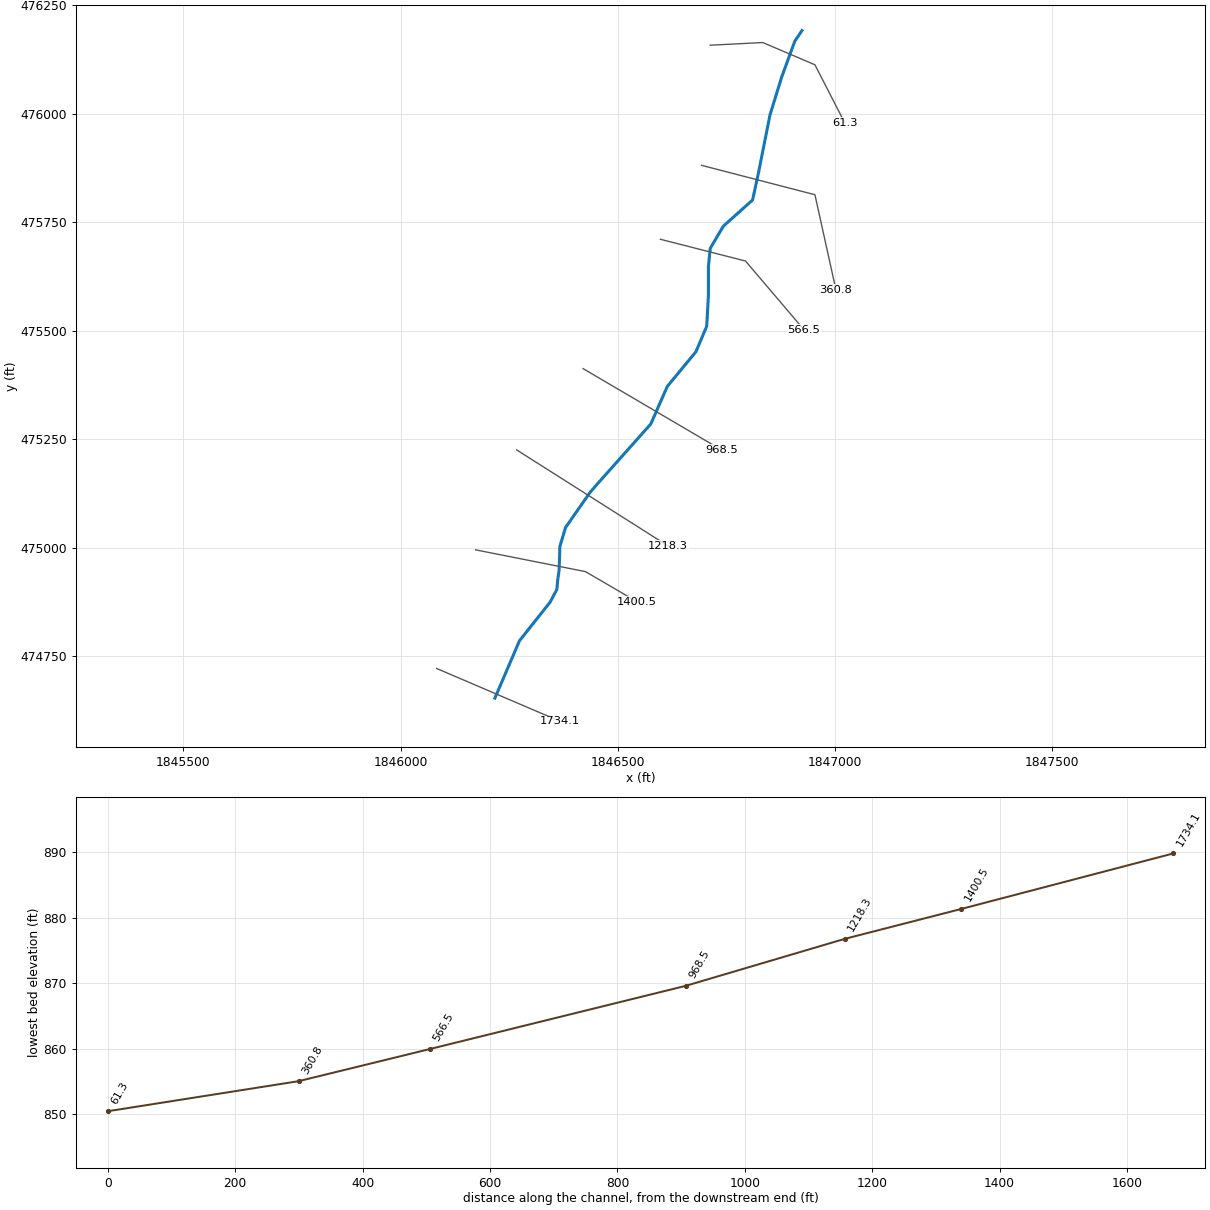
--- BGNINEMILE.prj (project) ---

Proj Title=BGNINEMILE
Current Plan=p01
Default Exp/Contr=0,0
English Units
Geom File=g01
Flow File=f01
Plan File=p01
BEGIN DESCRIPTION:
END DESCRIPTION:
DSS Export Rating Curves= 0
DSS Export Rating Curve Sorted= 0
DSS Export Volume Flow Curves= 0
DXF OffsetX= 0
DXF OffsetY= 0
DXF ScaleX= 0
DXF ScaleY= 0

--- BGNINEMILE.p01 (plan) ---

Plan Title=Floodplain
Program Version=4.00
Geom File=g01
Flow File=f01
K Sum by GR=0
Std Step Tol=0.01
Critical Tol=0.01
Num of Std Step Trials=20
Max Error Tol=0.3
Flow Tol Ratio=0.001
Split Flow NTrial=30
Split Flow Tol=0.02
Split Flow Ratio=0.02
Log Output Level=0
Friction Slope Method=1
Unsteady Friction Slope Method=2
Unsteady Bridges Friction Slope Method=1
Global Log Level=0
CheckData=False
Run HTab=0
Run UNet=0
Run PostProcess=0
UNET Theta=0
UNET Theta Warmup=0
UNET ZTol=0
UNET ZSATol=0
UNET MxIter=0
UNET MaxInSteps=0
UNET DtIC=0
UNET DtMin=0
UNET MaxCRTS=0
UNET WFStab=0
UNET SFStab=0
UNET WFX=0
UNET SFX=0
UNET DSS MLevel=0
UNET DZMax Abort=0
UNET Convert EG Bridges=0
UNET Use Existing IB Tables=0
UNET Froude Limit=0
UNET Froude Power=0
Write IC File=0
Echo Input=False
Echo Output=False
Write Detailed=0

--- BGNINEMILE.f01 (steady flow) ---

Flow Title=NFF Regression Equation
Program Version=4.10
Number of Profiles= 1
Profile Names=P100yr
River Rch & RM=BGNINEMILE,Main            ,1734.1
892.6851
River Rch & RM=BGNINEMILE,Main            ,566.5
926.5411
Boundary for River Rch & Prof#=BGNINEMILE,Main            , 1
Up Type= 0
Dn Type= 3
Dn Slope=0.015
DSS Import GetInterval= 0
DSS Import GetPeak= 0
DSS Import FillOption= 0

--- BGNINEMILE.g01 (geometry) ---

Geom Title=USGS 10m DEM
Program Version=4.10

River Reach=BGNINEMILE      ,Main
Reach XY= 25
     1846217.315      474653.932     1846273.922      474786.146
     1846344.376      474874.873     1846360.001      474904.387
     1846361.737      474924.352     1846365.209      474949.526
     1846366.946      475003.345     1846379.966      475046.748
     1846435.522      475126.609     1846451.682      475145.441
     1846576.147      475285.029     1846614.326      475371.773
     1846680.313      475451.696     1846705.053       475510.29
     1846708.959      475581.905     1846708.959      475648.311
     1846713.105      475689.567     1846743.364      475740.762
     1846810.351      475800.622     1846811.522      475804.709
     1846824.627      475865.319     1846850.669      475996.613
     1846877.796      476084.503     1846907.759      476166.401
     1846924.317      476191.026

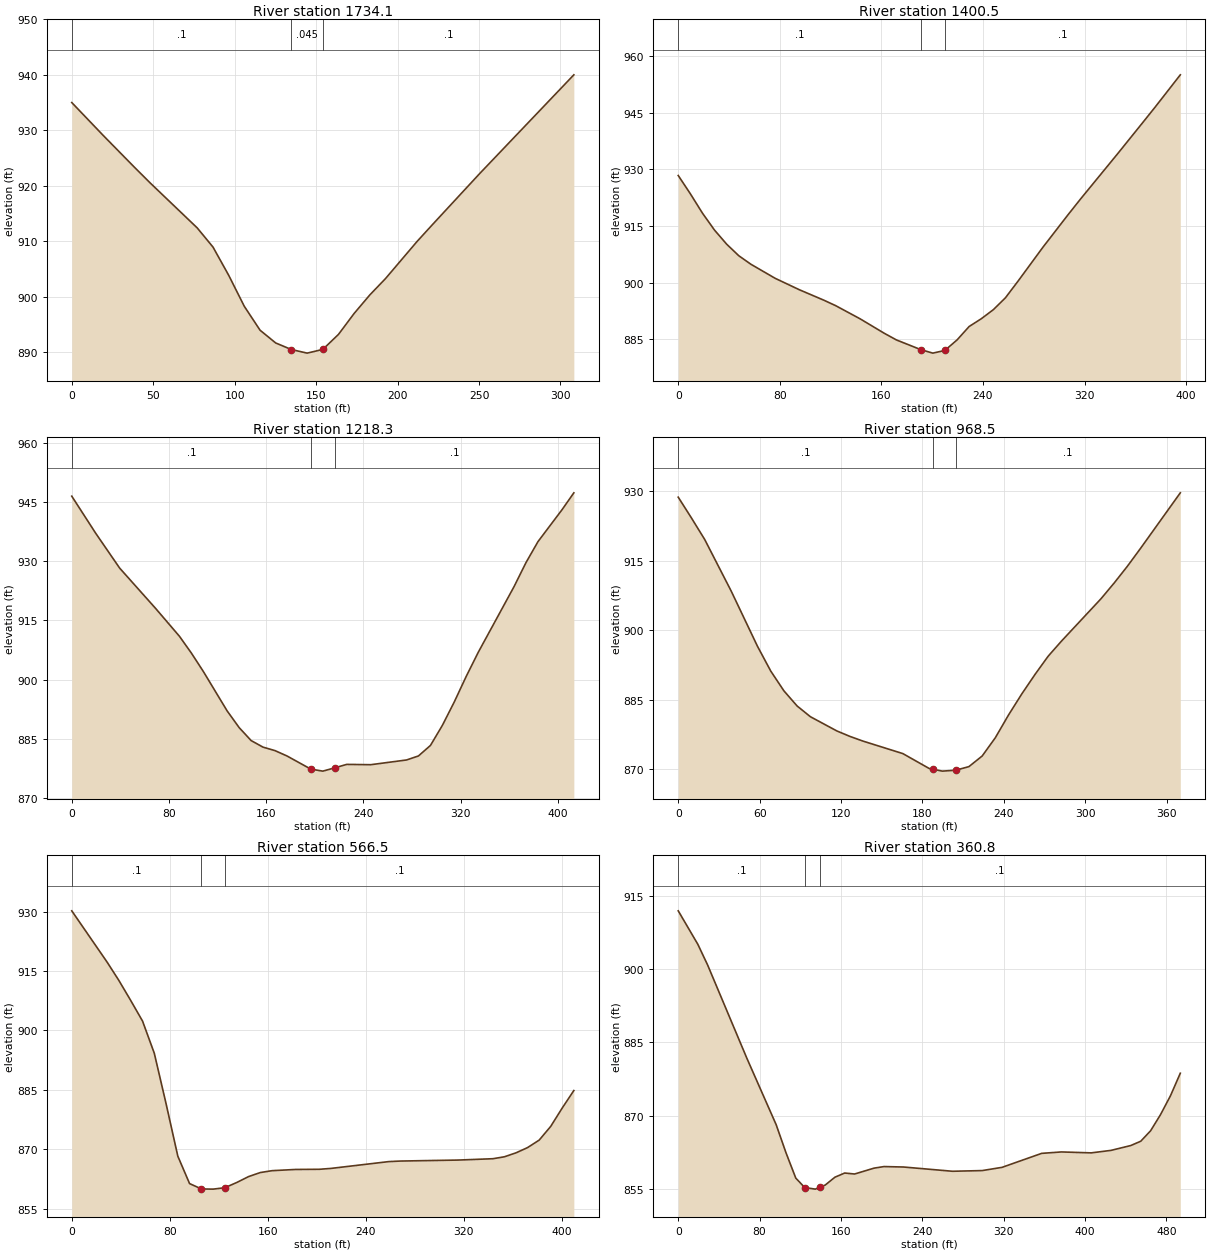
Type RM Length L Ch R = 1 ,1734.1  ,328.9,333.7,338.4
XS GIS Cut Line= 2
      1846083.07      474722.287     1846366.387      474600.986
#Sta/Elev= 21
       0     935    19.3  929.07    38.5  923.32    48.2  920.48      77  912.39
    86.7  908.93    96.3  903.86   105.9  898.25   115.6  893.93   125.2  891.63
   134.8  890.45   144.5   889.8   154.1  890.47   163.7  893.17   173.4  896.98
     183  900.31   192.6  903.25   211.9  909.92   221.5  913.01   250.4  922.19
   308.2     940
#Mann= 3 , 0 , 0
       0      .1       0   134.8    .045       0   154.1      .1       0
Bank Sta=134.8,154.1
XS Rating Curve= 0 ,0
Exp/Cntr=0.3,0.1

Type RM Length L Ch R = 1 ,1400.5  ,190.6,182.2,173.8
XS GIS Cut Line= 3
     1846173.031       474995.35     1846425.859      474945.274
     1846544.772      474875.831
#Sta/Elev= 30
       0  928.34     9.6  923.47    19.1  918.36    28.6  913.87    38.2  910.13
    47.7  907.09    57.3  904.82    76.4   901.1    95.5  898.07   114.6  895.33
   124.1  893.85   143.2  890.39   162.3  886.55   171.8   884.8   190.9  882.24
   200.5   881.3     210  882.02   219.6   884.8   229.1  888.35   238.6  890.39
   248.2  892.82   257.7  895.96   267.6  900.36   287.2  909.34   306.9  917.91
   316.8   922.1   346.3  934.21   365.9  942.39   375.8  946.55   395.4     955
#Mann= 3 , 0 , 0
       0      .1       0   190.9    .045       0     210      .1       0
Bank Sta=190.9,210
XS Rating Curve= 0 ,0
Exp/Cntr=0.3,0.1

Type RM Length L Ch R = 1 ,1218.3  ,249,249.8,250.6
XS GIS Cut Line= 2
     1846267.303      475225.572     1846616.261      475004.218
#Sta/Elev= 30
       0  946.53    19.7  937.12    39.4  928.28    68.9  918.08    88.6  910.98
    98.4  906.73   108.2  902.08   127.9  892.02   137.8  887.78   147.6  884.51
   157.4  882.84   167.3  881.95   177.1   880.6   196.8  877.25   206.6  876.75
   216.5  877.59   226.3  878.46     246  878.38   275.5  879.58   285.3   880.6
   295.2  883.27     305  888.36   314.8  894.31   324.7  900.84   334.5  906.89
     364  923.58   373.9  929.72   383.7     935   403.4  943.06   413.2  947.38
#Mann= 3 , 0 , 0
       0      .1       0   196.8    .045       0   216.5      .1       0
Bank Sta=196.8,216.5
XS Rating Curve= 0 ,0
Exp/Cntr=0.3,0.1

Type RM Length L Ch R = 1 ,968.5   ,395.5,402,408.4
XS GIS Cut Line= 2
     1846420.315      475412.679     1846739.394      475225.341
#Sta/Elev= 30
       0  928.73     9.7  924.26    19.5   919.6      39  908.47    58.4  896.53
    68.2  891.17    77.9   886.9    87.6  883.64    97.4  881.32   116.8  878.26
   126.6  877.06   136.3  876.04   165.5  873.36     185  870.13   187.9  869.96
   194.7  869.57   204.5  869.77   214.2  870.54     224  872.84   233.7  876.79
   243.4  881.69   253.2  886.25   262.9  890.44   272.6  894.38   282.4  897.64
   311.6  906.81   321.3  910.21   331.1  913.85   340.8  917.72     370  929.67
#Mann= 3 , 0 , 0
       0      .1       0   187.9    .045       0   204.5      .1       0
Bank Sta=187.9,204.5
XS Rating Curve= 0 ,0
Exp/Cntr=0.3,0.1

Type RM Length L Ch R = 1 ,566.5   ,205.5,205.7,206
XS GIS Cut Line= 3
     1846598.472      475710.445     1846794.305      475660.445
     1846929.027      475502.112
#Sta/Elev= 30
       0   930.2    28.9  917.23    38.5   912.6    48.1  907.58    57.8  902.35
    67.4  894.22      77   881.5    86.6  868.24    96.2  861.31   105.9  859.95
   115.5  859.91     125  860.27   134.7  861.58   144.4  863.08     154   864.1
   163.6  864.57   182.9  864.88   202.1  864.92   211.6  865.14   258.8  866.86
   268.3     867   315.5  867.25   343.9  867.59   353.3  868.08   362.8  869.08
   372.2   870.4   381.7  872.29   391.1  875.75   400.6  880.44     410  884.81
#Mann= 3 , 0 , 0
       0      .1       0   105.9    .045       0     125      .1       0
Bank Sta=105.9,125
XS Rating Curve= 0 ,0
Exp/Cntr=0.3,0.1

Type RM Length L Ch R = 1 ,360.8   ,302.8,299.5,296.1
XS GIS Cut Line= 3
     1846693.105      475880.753      1846954.17       475813.07
     1847002.515      475594.307
#Sta/Elev= 30
       0  911.89    19.3  905.04    28.9  900.82    67.4   881.8    96.3  868.18
     106  862.42   115.6  857.26   124.4  855.33   134.8  855.01   139.4   855.4
   144.5  855.84   154.1  857.45   163.7   858.3   173.4   858.1   192.6   859.3
   202.3  859.62   221.5  859.53   269.7  858.66   298.9   858.8   318.4  859.46
   357.4  862.32   376.8  862.61   406.1  862.42   425.6  862.93     445  863.92
   454.8   864.8   464.5  866.94   474.2  870.22     484  874.08   493.7   878.7
#Mann= 3 , 0 , 0
       0      .1       0   124.4    .045       0   139.4      .1       0
Bank Sta=124.4,139.4
XS Rating Curve= 0 ,0
Exp/Cntr=0.3,0.1

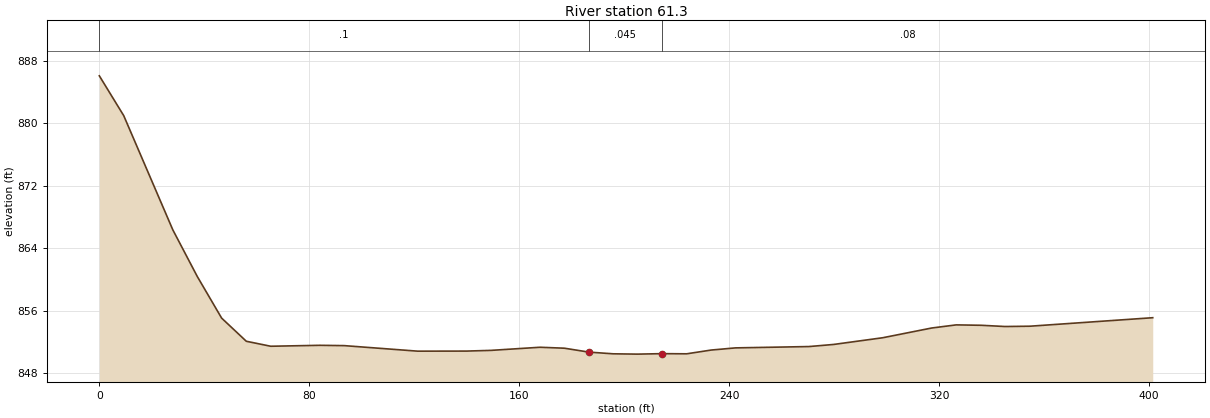
Type RM Length L Ch R = 1 ,61.3    ,65.6,61.3,57
XS GIS Cut Line= 4
     1846713.057      476157.325     1846834.169      476163.436
     1846954.182      476112.283     1847022.513      475979.163
#Sta/Elev= 30
       0  886.11     9.3     881      28  866.36    37.3  860.39    46.6  855.04
      56  852.07    65.3  851.43      84  851.55    93.3  851.51   121.3   850.8
   139.9  850.81   149.2   850.9   167.9   851.3   177.2  851.18   186.5  850.68
   195.8  850.46   205.1  850.42   214.4  850.48   223.8  850.46   233.1  850.94
   242.4  851.22   270.4  851.39   279.8  851.66   298.5  852.52   317.2  853.77
   326.5  854.17   335.9  854.12   345.2  853.96   354.6     854   401.4  855.09
#Mann= 3 , 0 , 0
       0      .1       0   186.5    .045       0   214.4     .08       0
Bank Sta=186.5,214.4
XS Rating Curve= 0 ,0
Exp/Cntr=0.3,0.1

Chan Stop Cuts=-1
Use User Specified Reach Order=0
Composite Channel Slope=5